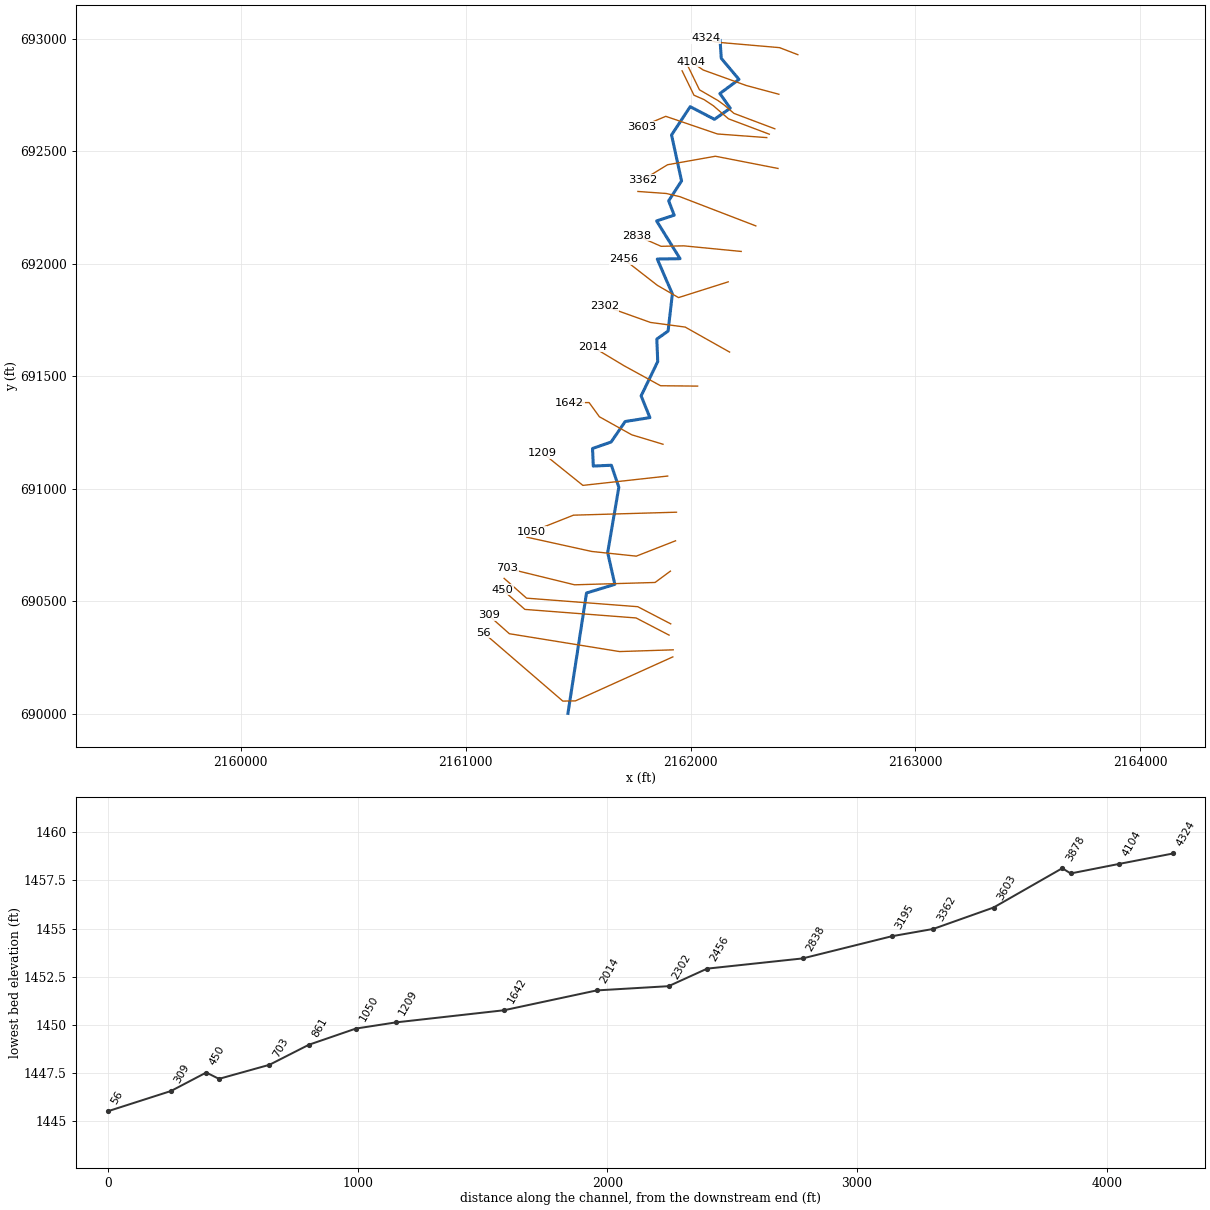
--- BEAVERRN.prj (project) ---

Proj Title=BEAVERRN
Current Plan=p01
Default Exp/Contr=0,0
English Units
Geom File=g01
Flow File=f01
Plan File=p01
BEGIN DESCRIPTION:
---------- MODELED AS PART OF WVEMD CTP PROGRAM, 2023----------
Stream Name: Full Stream Name (not code/AFG name)
Flood Zone:  AFH
Upshur County, WV
HEC-RAS Version: RAS 6.3
Vertical Datum: NAVD88
Projection: NAD 1983 StatePlane West Virginia S FIPS 4702 (US Feet)
Terrain: 1-meter LIDAR (FEMA Region III 3DEP collected 2016-2018)
Land Use: 2019 NLCD
Hydrologic Method:
WV SIR2010-5033 regression equations
Additional Model Notes:
Main stem is SLABCMPFK
END DESCRIPTION:
DSS Export Rating Curves= 0
DSS Export Rating Curve Sorted= 0
DSS Export Volume Flow Curves= 0
DXF OffsetX= 0
DXF OffsetY= 0
DXF ScaleX= 0
DXF ScaleY= 0

--- BEAVERRN.p01 (plan) ---

Plan Title=Floodplain
Program Version=6.31
Short Identifier=Floodplain
Geom File=g01
Flow File=f01
Subcritical Flow
K Sum by GR= 0
Std Step Tol= 0.01
Critical Tol= 0.01
Num of Std Step Trials= 20
Max Error Tol= 0.3
Flow Tol Ratio= 0.001
Split Flow NTrial= 30
Split Flow Tol= 0.02
Split Flow Ratio= 0.02
Log Output Level= 0
Friction Slope Method= 1
Unsteady Friction Slope Method= 2
Unsteady Bridges Friction Slope Method= 1
Parabolic Critical Depth
Global Vel Dist= 0 , 0 , 0
Global Log Level= 0
CheckData=True
Encroach Param=-1 ,0,0, 0
Mapping Interval=1HOUR
Computation Time Step Use Courant=        0
Computation Time Step Use Time Series=    0
Computation Time Step Count To Double=0
Computation Time Step Max Doubling=0
Computation Time Step Max Halving=0
Computation Time Step Residence Courant=0
Run HTab= 0
Run UNet= 0
Run Sediment= 0
Run PostProcess= 0
Run WQNet= 0
Run RASMapper=-1
UNET Theta= 0
UNET Theta Warmup= 0
UNET ZTol= 0
UNET ZSATol= 0
UNET MxIter= 0
UNET Max Iter WO Improvement= 0
UNET MaxInSteps= 0
UNET DtIC= 0
UNET DtMin= 0
UNET MaxCRTS= 0
UNET WFStab= 0
UNET SFStab= 0
UNET WFX= 1
UNET SFX= 1
UNET Gravity=32.17405
UNET 1D Methodology=Finite Difference
UNET DSS MLevel= 1
UNET Pardiso=0
UNET DZMax Abort= 0
UNET Use Existing IB Tables= 0
UNET Froude Reduction=False
UNET Froude Limit= 0
UNET Froude Power= 0
UNET D1 Cores= 0
UNET WindReference=Eulerian
UNET WindDragFormulation=Hsu (1988)
UNET D2 Coriolis=0
UNET D2 Cores= 0
UNET D2 Theta= 1
UNET D2 Theta Warmup= 1
UNET D2 Z Tol= 0.01
UNET D2 Volume Tol= 0.01
UNET D2 Max Iterations= 20
UNET D2 Equation= 0
UNET D2 RampUpFraction=0.1
UNET D2 TimeSlices= 1
UNET D2 Turbulence Formulation=Non-Conservative (original)
UNET D2 Eddy Viscosity=0.3
UNET D2 Transverse Eddy Viscosity=0.1
UNET D2 Smagorinsky Mixing=0
UNET D2 BCVolumeCheck=0
UNET D2 Cores=0
UNET D2 SolverType=PARDISO (Direct)
UNET D2 Minimum Iterations= 3
UNET D2 Maximum Iterations= 30
UNET D2 Restart Number= 10
UNET D2 Relaxation Coeff=1.3
UNET D2 SOR Precondition Iterations= 10
UNET D2 ILUT Maximum Fill= 8
UNET D2 ILUT Tolerance=1E-08
UNET D2 Convergence Tolerance=0.00001
UNET D1D2 MaxIter= 0
UNET D1D2 ZTol=0.01
UNET D1D2 QTol=0.1
UNET D1D2 MinQTol=1
Write IC File= 0
Write IC File at Fixed DateTime=0
Write IC File at Sim End=0
Echo Input=False
Echo Parameters=False
Echo Output=False
Write Detailed= 0
HDF Write Warmup=0
HDF Write Time Slices=0
HDF Flush=0
HDF Compression= 1
HDF Chunk Size= 1
HDF Spatial Parts= 1
HDF Use Max Rows=0
HDF Fixed Rows= 1
Calibration Method= 0
Calibration Iterations= 20
Calibration Max Change=0.05
Calibration Tolerance=0.2
Calibration Maximum=1.5
Calibration Minimum=0.5
Calibration Optimization Method= 1
WQ AD Non Conservative
WQ ULTIMATE=-1
WQ Max Comp Step=1HOUR
WQ Output Interval=15MIN
WQ Output Selected Increments= 0
WQ Create Restart=0
WQ Fixed Restart=0
WQ System Summary=0
WQ Write To DSS=0
Sorting and Armoring Iterations= 10
XS Update Threshold= 0.02
Bed Roughness Predictor= 0
Hydraulics Update Threshold= 0.02
Energy Slope Method= 1
Volume Change Method= 1
Sediment Retention Method= 0
Sediment TS Multiplier= 1
Warm Up Method= 0
XS Weighting Method= 0
Number of US Weighted Cross Sections= 1
Number of DS Weighted Cross Sections= 1
Upstream XS Weight=0
Main XS Weight=1
Downstream XS Weight=0
Number of DS XS's Weighted with US Boundary= 1
Upstream Boundary Weight= 1
Weight of XSs Associated with US Boundary= 0
Number of US XS's Weighted with DS Boundary= 1
Downstream Boundary Weight= 0.5
Weight of XSs Associated with DS Boundary= 0.5
Percentile Method= 0
Sediment Output Level= 3
Mass or Volume Output= 0
Output Increment Type= 1
Profile and TS Output Increment= 1
Transport Output Increment 1
XS Output Flag= 0
XS Output Increment= 10
Read HDF5 Sediment Hotstart= 0
Sediment Hotstart Type= 0
Write Gradation File= 0
Read Gradation Hotstart= 0
Write HDF5 File= 1
Write Binary Output= 1
Write DSS Sediment File= 0
DSS Sediment Output Type= 1
SV Curve= 0
Specific Gage Flag= 0
Subcell Erosion Methods= 0
Subcell Deposition Methods= 0
Advection Scheme= 1
Matrix Solver= 0
Implicit Weighting Factor= 1
Maximum Outer Loop Convergence Iterations= 5
Convergence Maximum Absolute= 0.001
Convergence RMSE= 0.0001
Grain Fractions Max Abs Error= 0.001
Max Subgrid Regions= 1
Max Subgrid Length Scale= 3.402823E+38
Initial Layer Thickness= 3.402823E+38
Min Layer Thickness= 3.402823E+38
Max Layer Thickness= 3.402823E+38
Number of Layers= 5

--- BEAVERRN.f01 (steady flow) ---

Flow Title=Flows
Program Version=6.31
Number of Profiles= 1
Profile Names=01pct
River Rch & RM=BEAVERRN,Main,4324
     291
Boundary for River Rch & Prof#=BEAVERRN,Main            , 1
Up Type= 0
Dn Type= 3
Dn Slope=0.00414
DSS Import GetInterval= 0
DSS Import GetPeak= 0
DSS Import FillOption= 0

--- BEAVERRN.g01 (geometry) ---

Geom Title=Geometry
Program Version=6.31

River Reach=BEAVERRN        ,Main
Reach XY= 30
2162131.46992204692992.630217042 2162136.5866591692913.320792605
2162215.38440983692819.6845043992162130.44657463692756.748638555
2162176.49720817692691.7660778872162106.39791044  692642.1337284
2161998.43475847692698.4178360662161915.54361809692572.546104378
2161960.05923051692368.3882956662161902.75177544 692279.86874452
2161927.31211333692215.909531264 2161849.0260363692190.325845962
2161953.40747234692022.4968703782161852.09607854 692020.96184926
2161919.12533403691865.9247163282161900.19340691691700.654109275
2161850.04938371691664.8369498522161854.14277336691565.060577173
2161780.26997888691412.3903896482161819.34896135691315.875482328
2161709.33911455691298.4785763222161646.91492241691207.400656646
2161564.18048364691178.4680211182161567.60549798691100.460852083
2161647.93826983691104.0425680252161681.19706072 691006.31289017
2161631.49343509690715.9746466592161663.38580135690574.305398636
 2161537.4948819690536.034559123     2161454.835      690000.714

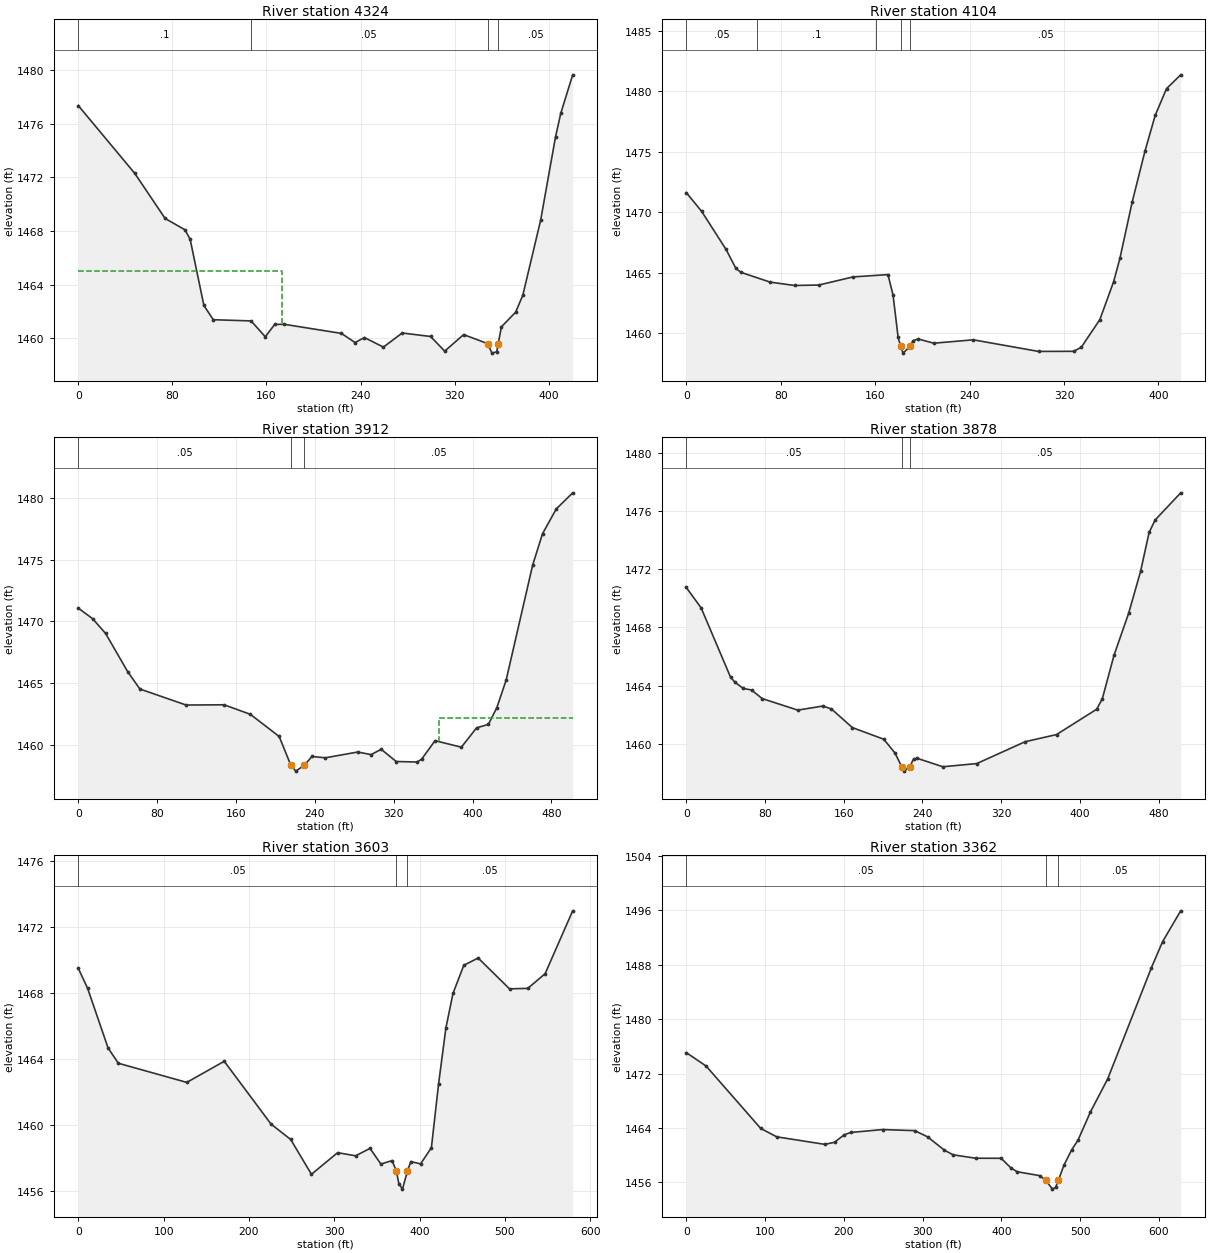
Type RM Length L Ch R = 1 ,4324    ,219.4,219.4,219.4
XS GIS Cut Line= 4
2162477.07504913692929.6213049042162395.95024176692960.860591569
2162111.56669829692985.5125297222162066.66562629693002.269355315
#Sta/Elev= 30
       0 1477.35    48.1 1472.29    73.8 1468.94    90.7 1468.09    95.1 1467.39
   106.8 1462.45   114.8 1461.39   146.9  1461.3     159 1460.12     167 1461.04
     175 1461.05   223.7 1460.37   235.3 1459.69   243.3 1460.06   259.4 1459.35
   275.4  1460.4   299.5 1460.14   311.5 1459.05   327.6 1460.28   347.91459.613
   351.7  1458.9   355.7    1459  356.99  1459.6   359.7 1460.86   371.8 1461.95
   377.9 1463.21   393.1 1468.82   405.7 1475.01   410.2 1476.78   420.3 1479.64
#Mann= 4 ,-1,0
       0      .1       0  146.93     .05       0   347.9    .045       0
  356.99     .05       0
#XS Ineff= 2 , 0
          173.52 1465.02
Permanent Ineff=
       F       F
Bank Sta=347.9,356.99
XS Rating Curve= 0 ,0
Exp/Cntr=0.3,0.1

Type RM Length L Ch R = 1 ,4104    ,195.1,192.1,185.7
XS GIS Cut Line= 4
 2162392.7669079692753.6309042262162247.27257319692792.710722465
2162056.21195105692861.5214022772162002.28822252692898.116530043
#Sta/Elev= 30
       0 1471.62      13 1470.07    33.7 1466.92      42 1465.36    46.2 1465.03
      71 1464.22    91.7 1463.94   112.4 1463.98   141.4 1464.65   170.9 1464.84
   175.2 1463.14   179.5 1459.65   181.6 1458.92   183.7 1458.35  189.751458.931
   192.2 1459.38   196.5 1459.52   209.7 1459.17   243.2 1459.45   298.5 1458.49
   328.3  1458.5   334.7 1458.84   350.4 1461.12   362.1 1464.26   367.4 1466.18
   377.9 1470.88   388.7 1475.07   397.3    1478   406.9 1480.21   418.9 1481.35
#Mann= 5 ,-1,0
       0     .05       0      60      .1       0  160.65     .05       0
   181.6    .045       0  189.75     .05       0
Bank Sta=181.6,189.75
XS Rating Curve= 0 ,0
Exp/Cntr=0.3,0.1

Type RM Length L Ch R = 1 ,3912    ,34.2,33.7,33.1
XS GIS Cut Line= 6
2162374.68775394692600.0734511812162193.05588786 692668.53761695
2162148.94744368692706.2821235542162122.25491892 692725.56478967
 2162039.6808767692773.3730421652161986.82576947692882.040823265
#Sta/Elev= 30
       0 1471.08    14.6 1470.22    27.7 1469.03    50.1 1465.93    62.5 1464.52
   109.4 1463.22   147.9 1463.24   174.5 1462.47   203.8 1460.67   215.6 1458.34
   220.7 1457.86   229.3 1458.34   237.1 1459.05   250.6 1458.94   283.5 1459.41
     297  1459.2   307.3 1459.63   322.5 1458.64   343.7  1458.6   348.3 1458.83
   361.9 1460.33   388.6  1459.8     404 1461.37     416 1461.65   424.6 1463.01
     434 1465.24   460.9 1474.57   470.9 1477.11   484.8 1479.12   501.5 1480.43
#Mann= 3 ,-1,0
       0     .05       0   215.6    .045       0   229.3     .05       0
#XS Ineff= 2 , 0
                          365.67         1462.17
Permanent Ineff=
       F       F
Bank Sta=215.6,229.3
XS Rating Curve= 0 ,0
Exp/Cntr=0.3,0.1

Type RM Length L Ch R = 1 ,3878    ,270.9,275.4,279.3
XS GIS Cut Line= 6
 2162350.3073109692576.0137853632162168.67544482692644.477951133
2162101.65191834692702.3445555122162060.15153432692729.812897803
2162015.30043366692749.3133763482161962.44532643692857.981157447
#Sta/Elev= 30
       0 1470.74    15.1 1469.34      45 1464.58    49.4 1464.24    57.8 1463.81
    66.3  1463.7    77.2 1463.11   113.3 1462.32   138.9  1462.6   147.5  1462.4
   168.8 1461.12   200.7 1460.32   212.1 1459.38  219.071458.418   221.3 1458.13
     227 1458.42   231.1 1458.97   234.7 1459.01   260.8 1458.43   295.3 1458.65
   344.4 1460.15   376.3 1460.64   417.1 1462.38   422.8 1463.09   434.7 1466.08
   449.7 1468.99   461.7 1471.84   470.4 1474.52   476.6 1475.38   502.5 1477.24
#Mann= 3 ,-1,0
       0     .05       0  219.07    .045       0     227     .05       0
Bank Sta=219.07,227
XS Rating Curve= 0 ,0
Exp/Cntr=0.3,0.1

Type RM Length L Ch R = 1 ,3603    ,231.6,241.4,254.5
XS GIS Cut Line= 4
2162339.03284104692560.834882069 2162119.6411824      692577.006
 2161889.8525554692655.4833786832161782.41119998692610.021306189
#Sta/Elev= 30
       0 1469.48    10.9 1468.27      35 1464.64      47 1463.72   127.2 1462.56
   171.1 1463.84     226 1460.03     249  1459.1   273.3 1456.99     304  1458.3
   325.1 1458.11     342 1458.56   354.7 1457.61   367.8 1457.82   372.9 1457.18
   375.8 1456.41     380 1456.09  385.771457.182   389.8 1457.76   401.2 1457.62
   413.9  1458.6   422.3 1462.46   430.9 1465.86   439.2 1467.95   451.9 1469.66
   468.7  1470.1   505.5 1468.23   526.9 1468.26   547.2 1469.15   579.5 1472.96
#Mann= 3 ,-1,0
       0     .05       0   372.9    .045       0  385.77     .05       0
Bank Sta=372.9,385.77
XS Rating Curve= 0 ,0
Exp/Cntr=0.3,0.1

Type RM Length L Ch R = 1 ,3362    ,170.3,166.3,160.5
XS GIS Cut Line= 4
2162388.89823648692423.7370156282162110.65179673692478.027001954
2161897.87294765692440.2281597062161788.49620389692373.460288608
#Sta/Elev= 30
       0 1475.08    25.2  1473.1    94.5 1463.92   114.8 1462.68     176 1461.57
   188.2 1461.88   200.4 1462.97   208.6 1463.32   249.3 1463.75   290.1 1463.59
   306.3 1462.68   327.8 1460.71   338.8 1460.03   367.3 1459.53   399.8 1459.52
     412 1458.12   420.1 1457.54   448.5 1456.97   456.6 1456.27   464.8 1454.98
   468.8 1455.22  472.411456.282   479.5 1458.51   489.1 1460.73   497.3 1462.18
   513.1 1466.34   535.1 1471.23   590.6  1487.6   604.7 1491.41   627.7 1495.95
#Mann= 3 ,-1,0
       0     .05       0   456.6    .045       0  472.41     .05       0
Bank Sta=456.6,472.41
XS Rating Curve= 0 ,0
Exp/Cntr=0.3,0.1

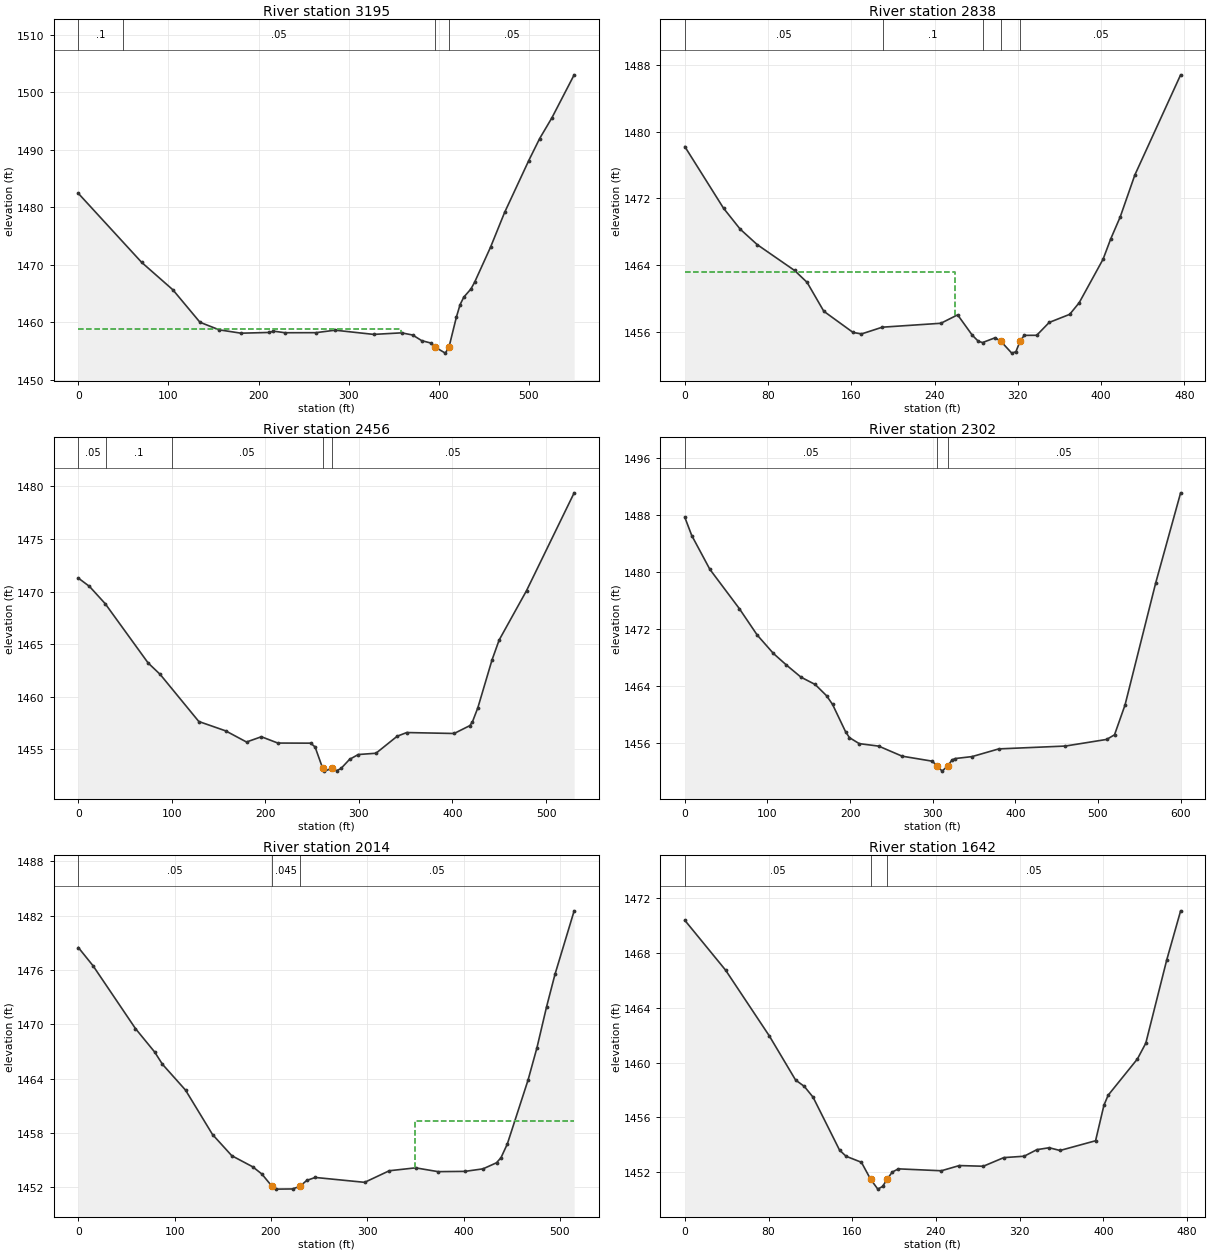
Type RM Length L Ch R = 1 ,3195    ,355.3,356.8,361.6
XS GIS Cut Line= 4
2162290.15158829692168.340152662 2161952.1987896692298.355162548
2161891.47239491692312.5026569572161765.92607751692321.375272298
#Sta/Elev= 30
       0  1482.4    70.3 1470.39     105 1465.61     135 1459.97   156.4 1458.65
   180.6 1458.07   212.1  1458.2   216.4 1458.43   229.3 1458.15   263.6 1458.16
     285 1458.59   327.8 1457.86   358.8 1458.13   371.1 1457.75   381.1 1456.77
   390.9 1456.37   395.8 1455.66   407.3  1454.6   411.4 1455.66   419.6 1460.88
   423.7 1463.04   427.8 1464.34   435.7 1465.76   439.8 1466.93   457.5 1473.04
   473.1 1479.08   499.9 1488.11     512 1491.94   525.6 1495.55   550.3 1503.03
#Mann= 4 ,-1,0
       0      .1       0      50     .05       0   395.8    .045       0
   411.4     .05       0
#XS Ineff= 2 , 0
          357.88 1458.73
Permanent Ineff=
       F       F
Bank Sta=395.8,411.4
XS Rating Curve= 0 ,0
Exp/Cntr=0.3,0.1

Type RM Length L Ch R = 1 ,2838    ,372.1,382.3,366.3
XS GIS Cut Line= 4
2162225.15681768692054.7205594242161970.26588036692079.551033813
2161869.04684458  692077.52189052161759.96376646692125.393852281
#Sta/Elev= 30
       0 1478.22    37.2 1470.83    53.2 1468.32    69.6 1466.46   105.5 1463.36
   117.5 1461.94   133.6 1458.47   161.7 1455.93   169.8 1455.75   189.8 1456.56
   246.1 1457.03   262.2 1458.04   276.2 1455.61   282.2 1454.86   286.2 1454.72
   298.2 1455.29   303.6 1454.89   314.2 1453.45   318.2 1453.62   322.2 1454.88
   326.2 1455.58   338.2 1455.59   350.2 1457.13   369.9  1458.1     379 1459.49
     402 1464.72   409.3 1467.14   418.5  1469.8   432.5 1474.81   476.5 1486.82
#Mann= 5 ,-1,0
       0     .05       0     190      .1       0   286.1     .05       0
   303.6    .045       0   322.2     .05       0
#XS Ineff= 2 , 0
             260 1463.12
Permanent Ineff=
       F       F
Bank Sta=303.6,322.2
XS Rating Curve= 0 ,0
Exp/Cntr=0.3,0.1

Type RM Length L Ch R = 1 ,2456    ,150.8,154.5,163.6
XS GIS Cut Line= 4
2162167.54375994691919.4933547522161946.59166008691849.474808582
2161852.47143782691903.9676314562161702.93333082692020.482249158
#Sta/Elev= 30
       0 1471.28    11.9 1470.49    28.7 1468.85    74.6 1463.21    87.5 1462.12
   128.8 1457.64   157.5 1456.75   179.8 1455.69   195.7 1456.19   213.3 1455.59
   248.4 1455.58   253.1 1455.22   261.2  1453.2   263.1 1452.92   271.1 1453.18
   276.2 1452.96   280.8 1453.17     290 1454.04   299.3  1454.5   318.2 1454.62
   340.9 1456.24   351.1 1456.59   401.8  1456.5   418.6 1457.25   421.4 1457.62
   427.1 1458.94   442.3  1463.5   449.9 1465.39   479.2 1470.09   530.1 1479.39
#Mann= 5 ,-1,0
       0     .05       0      30      .1       0     100     .05       0
   261.2    .045       0   271.1     .05       0
Bank Sta=261.2,271.1
XS Rating Curve= 0 ,0
Exp/Cntr=0.3,0.1

Type RM Length L Ch R = 1 ,2302    ,288.4,287.8,278.6
XS GIS Cut Line= 4
2162173.69252704691607.2197328812161976.22966005691718.382179018
2161821.85769381691738.9845120292161616.78895569 691812.24310878
#Sta/Elev= 30
       0 1487.64     8.4 1485.08    30.3 1480.34      66 1474.82    87.7  1471.1
   107.3 1468.52     123  1466.9   140.6  1465.2   157.8 1464.17   171.6 1462.59
   178.8 1461.38   194.5 1457.56   199.3 1456.71   211.1 1455.87   234.7 1455.52
     263 1454.11   299.3 1453.41  305.811452.714   311.4 1452.01  317.991452.711
   323.5 1453.59   327.5 1453.78   347.7 1454.05     380 1455.13   460.6 1455.53
   510.6 1456.46   520.1 1457.11   532.8 1461.29     570 1478.45   600.1 1491.07
#Mann= 3 ,-1,0
       0     .05       0  305.81    .045       0  317.99     .05       0
Bank Sta=305.81,317.99
XS Rating Curve= 0 ,0
Exp/Cntr=0.3,0.1

Type RM Length L Ch R = 1 ,2014    ,363.5,371.3,364.8
XS GIS Cut Line= 4
2162031.49424869691455.9008559072161866.72175486691457.560625287
2161704.35820125691546.5026740362161563.05884996691631.347689137
#Sta/Elev= 30
       0 1478.47    15.3 1476.45    59.3 1469.52    79.3 1466.92    87.3 1465.58
   111.3 1462.72   139.3 1457.82   159.3 1455.48   181.1 1454.25   190.5 1453.46
  200.811452.132   205.6 1451.79   222.4 1451.81  230.121452.109   237.1 1452.75
   245.9 1453.08   297.2 1452.54   322.8 1453.82   350.1 1454.14   373.5 1453.72
   401.4 1453.75   420.1 1454.03   434.1  1454.7   438.8 1455.27   445.3 1456.77
   466.8 1463.82   476.1 1467.41   486.1 1471.94   494.8 1475.51   514.7 1482.52
#Mann= 3 ,-1,0
       0     .05       0  200.81    .045       0  230.12     .05       0
#XS Ineff= 2 , 0
                          349.86          1459.3
Permanent Ineff=
       F       F
Bank Sta=200.81,230.12
XS Rating Curve= 0 ,0
Exp/Cntr=0.3,0.1

Type RM Length L Ch R = 1 ,1642    ,415.1,433.1,439.6
XS GIS Cut Line= 5
 2161877.5111935691197.4160371172161738.55479282691239.406850812
  2161594.771049691319.548641593 2161548.9644249691382.730192076
2161462.84001563691381.770048222
#Sta/Elev= 30
       0 1470.38      39 1466.74    80.8 1461.94   105.9 1458.72   114.2 1458.26
   122.6 1457.47   147.9 1453.61   154.1 1453.16   168.8 1452.72   177.6 1451.48
   184.5 1450.76   189.1 1450.96  193.241451.464   198.2    1452   204.1 1452.24
   245.2  1452.1   262.4 1452.48   285.3 1452.43   304.9 1453.06   324.3 1453.16
   336.5 1453.64   348.3 1453.78   358.6 1453.58   392.6 1454.29   400.6 1456.88
   404.6 1457.61   432.6 1460.26   440.6 1461.41   460.6 1467.48   473.9 1471.07
#Mann= 3 ,-1,0
       0     .05       0   177.6    .045       0  193.24     .05       0
Bank Sta=177.6,193.24
XS Rating Curve= 0 ,0
Exp/Cntr=0.3,0.1

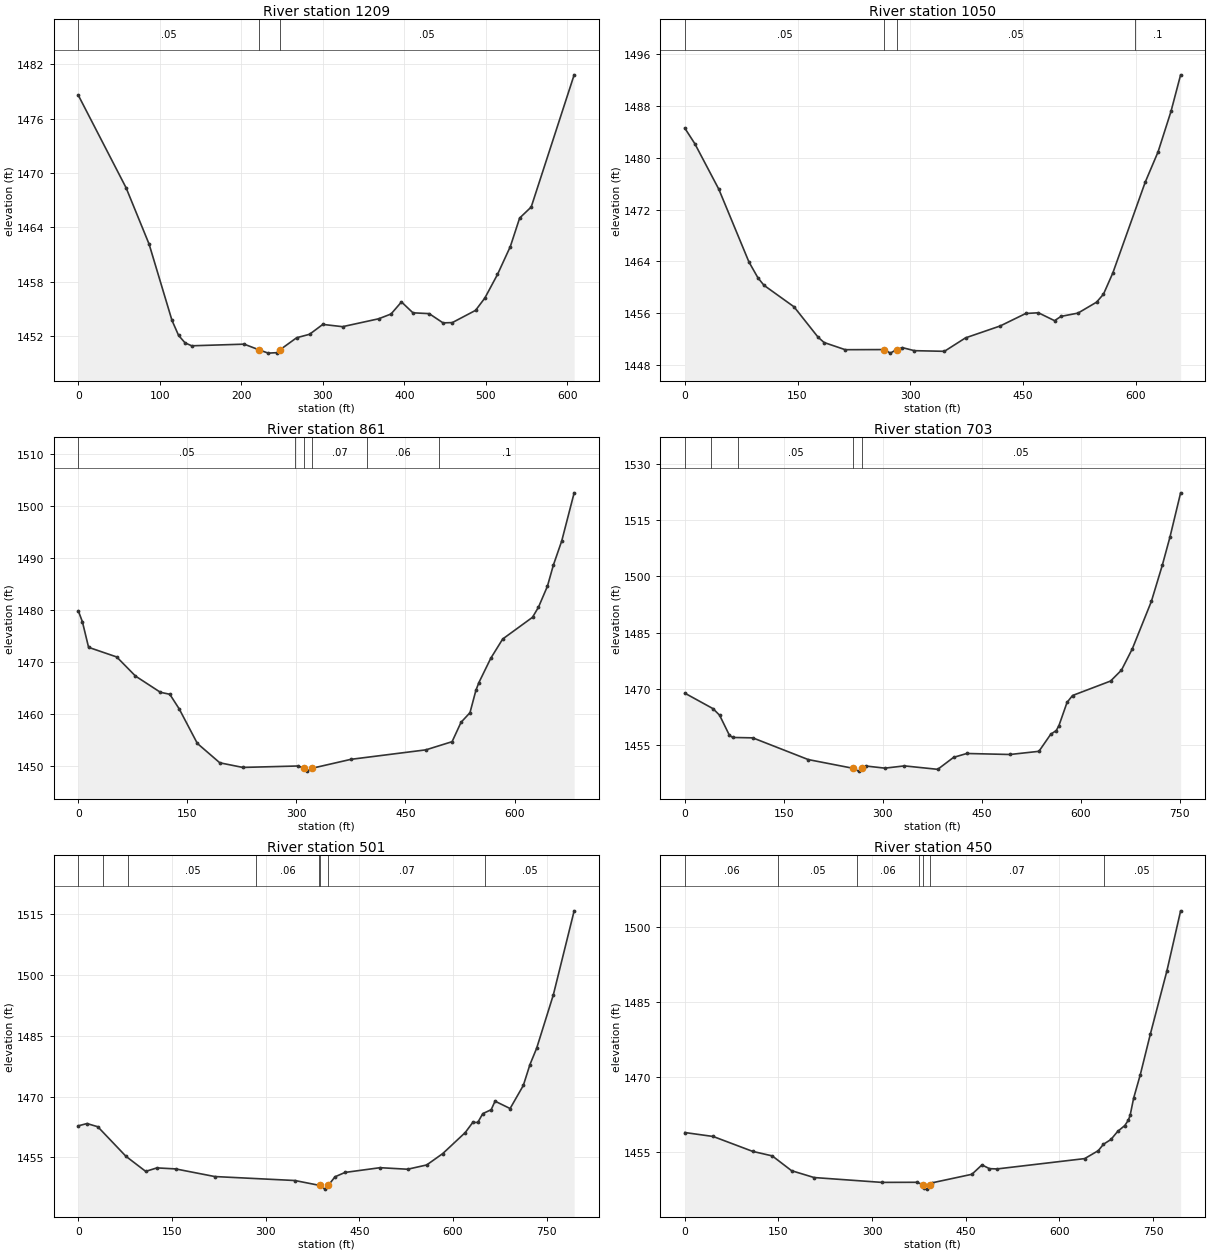
Type RM Length L Ch R = 1 ,1209    ,154,159.8,157.1
XS GIS Cut Line= 3
 2161898.4166606691056.008327678 2161521.3001277691014.461691857
2161342.83986839691158.025669031
#Sta/Elev= 30
       0 1478.59    58.6 1468.38    86.8 1462.17   114.9 1453.75     123 1452.09
     131 1451.26   139.1 1450.94   203.5 1451.12   222.1 1450.48     233 1450.13
   243.5 1450.18  247.091450.476   267.9 1451.83   283.7 1452.21     300  1453.3
   324.2 1453.05   368.5 1453.92   383.7 1454.45   396.5 1455.78   410.6 1454.58
   430.5 1454.49   447.5 1453.47   458.9  1453.5   487.4 1454.85   498.8 1456.21
   514.3 1458.81   530.1  1461.9   541.5 1465.04   555.7 1466.26   608.4 1480.85
#Mann= 3 ,-1,0
       0     .05       0   222.1    .045       0  247.09     .05       0
Bank Sta=222.1,247.09
XS Rating Curve= 0 ,0
Exp/Cntr=0.3,0.1

Type RM Length L Ch R = 1 ,1050    ,188.9,188.4,185.2
XS GIS Cut Line= 3
2161937.44432422690895.2276782442161479.46471937690882.016404497
2161292.24685733690807.969827873
#Sta/Elev= 30
       0  1484.6    13.3  1482.2    45.3 1475.14    85.3 1463.91    97.3 1461.45
   105.3  1460.3   145.3 1456.97   177.3 1452.27   185.3 1451.45   213.4 1450.34
   265.4 1450.36   273.4 1449.81  281.67 1450.36   289.4 1450.66   305.4 1450.19
   345.3 1450.09   373.4 1452.17   419.5 1454.01   453.5 1455.94   470.3 1456.05
   491.8 1454.83   500.4 1455.49     523    1456   547.7 1457.69   556.9 1458.93
   569.3  1462.2   612.4 1476.24   629.5 1480.93   646.7 1487.19   659.5 1492.84
#Mann= 4 ,-1,0
       0     .05       0   265.4    .045       0  281.67     .05       0
  598.17      .1       0
Bank Sta=265.4,281.67
XS Rating Curve= 0 ,0
Exp/Cntr=0.3,0.1

Type RM Length L Ch R = 1 ,861     ,154,157.8,157.8
XS GIS Cut Line= 4
 2161933.3504023690768.0739033822161758.71727766690699.856532957
2161560.63100547690720.6754537072161272.17885662690784.156598981
#Sta/Elev= 30
       0 1479.76     5.6 1477.67    14.1 1472.76    52.8 1470.91    78.6 1467.24
   112.9 1464.12   125.8 1463.74   138.7 1460.94   163.7 1454.29   194.6 1450.57
   226.2 1449.68   302.7 1449.96   310.2 1449.52   314.7 1448.97  321.961449.536
   375.1 1451.24   478.1 1453.06   514.1 1454.63   526.4 1458.35   538.7  1460.2
   546.9 1464.52     551    1466   567.3 1470.66   583.7 1474.36   624.7 1478.53
   632.9 1480.47   645.2 1484.49   653.4 1488.56   664.9  1493.2     682 1502.45
#Mann= 6 ,-1,0
       0     .05       0  297.48     .07       0   310.2    .045       0
  321.96     .07       0  396.66     .06       0  496.66      .1       0
Bank Sta=310.2,321.96
XS Rating Curve= 0 ,0
Exp/Cntr=0.3,0.1

Type RM Length L Ch R = 1 ,703     ,204.3,202.2,200.7
XS GIS Cut Line= 4
2161910.56862792690633.2249471942161842.18322246690582.773531411
2161484.44255364690572.3940454622161185.16757967690645.601681031
#Sta/Elev= 30
       0 1468.79    42.7 1464.65    52.7 1462.89    67.6 1457.51    72.6 1456.94
     103 1456.83     187 1451.02   255.1 1448.68   263.1 1447.93  268.241448.665
   275.1 1449.28   303.1 1448.73   332.7 1449.33   383.1 1448.41   407.1 1451.61
   427.1 1452.65   492.6 1452.38   536.4 1453.23   554.3 1457.81   562.6 1458.78
   566.7 1460.12     579 1466.33   587.3 1468.16   644.9 1472.03   661.4 1474.95
   677.9 1480.68   706.7 1493.34   723.2 1502.98   734.9 1510.58     751 1522.38
#Mann= 5 ,-1,0
       0     .06       0      40     .07       0      80     .05       0
   255.1    .045       0  268.24     .05       0
Bank Sta=255.1,268.24
XS Rating Curve= 0 ,0
Exp/Cntr=0.3,0.1

Type RM Length L Ch R = 1 ,501     ,50.6,50.8,50.7
XS GIS Cut Line= 5
2161911.87235561690398.781596145 2161765.2266874690475.061235536
2161460.46698839690498.514451076 2161270.7493921690513.097950559
2161171.12289674690600.991518754
#Sta/Elev= 30
       0 1462.79    13.9 1463.35    31.2 1462.56    76.3 1455.28   107.9 1451.57
   125.9 1452.43   155.8 1452.18   218.5  1450.3   346.9 1449.32     387  1448.1
     395  1447.2  400.271448.113   411.1 1450.24   427.1 1451.31   483.3 1452.48
   527.4  1452.1   557.9 1453.15   583.6 1455.95   619.7 1461.14   631.7 1463.63
   639.7 1463.62   647.8  1465.8   661.2 1466.76   667.4 1468.86   691.5 1467.05
   712.7 1472.74   723.3 1477.88     734 1481.89   760.7 1495.02   794.1 1515.74
#Mann= 8 ,-1,0
       0     .06       0      40     .07       0      80     .05       0
   285.3     .06       0   385.3     .07       0     387    .045       0
  400.27     .07       0  650.96     .05       0
Bank Sta=387,400.27
XS Rating Curve= 0 ,0
Exp/Cntr=0.3,0.1

Type RM Length L Ch R = 1 ,450     ,141.9,141.3,140.1
XS GIS Cut Line= 5
2161904.47711108690348.7221353572161757.83144287690425.001774748
2161453.07174385690448.4549902882161263.35414757690463.038489771
 2161163.7276522690550.932057967
#Sta/Elev= 30
       0 1458.86    45.4 1458.07   108.6 1455.09   140.1 1454.18     171 1451.22
   207.1 1449.85   315.4 1448.88   371.9  1448.9  380.731448.443   383.6 1447.75
   387.6 1447.53   392.9 1448.43   395.6 1448.78   459.8  1450.5   475.9 1452.38
   487.9 1451.63   499.9 1451.57   640.4 1453.64   662.2 1455.23   670.5 1456.51
   682.6 1457.48   693.3 1459.09   704.7 1460.26   710.3 1461.32   713.2 1462.28
   718.8 1465.72   729.5 1470.43   745.5 1478.51   772.2 1491.25   794.1 1503.24
#Mann= 7 ,-1,0
       0     .06       0     150     .05       0   275.3     .06       0
   375.3     .07       0  380.73    .045       0   392.9     .07       0
  671.24     .05       0
Bank Sta=380.73,392.9
XS Rating Curve= 0 ,0
Exp/Cntr=0.3,0.1

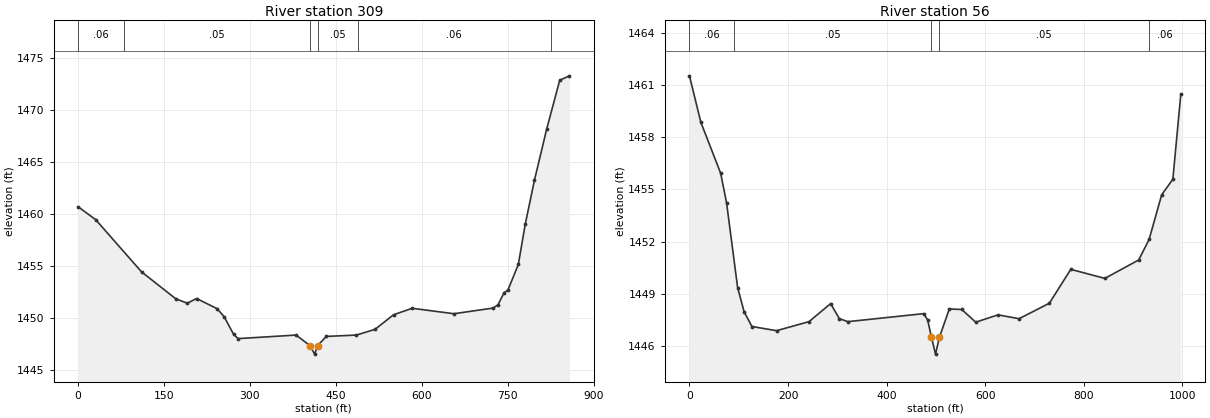
Type RM Length L Ch R = 1 ,309     ,252.7,252.7,252.7
XS GIS Cut Line= 4
2161922.84264734690283.242188468 2161684.3153915690275.550043399
2161194.41260159690354.8715814252161102.43393718690436.455067678
#Sta/Elev= 30
       0 1460.72    30.7 1459.48   110.7 1454.47   170.8 1451.87   190.8 1451.46
   206.8 1451.91   242.8 1450.93     255 1450.16   271.6 1448.46   279.3 1448.06
   380.6  1448.4   404.9 1447.38     413 1446.57   418.1 1447.38   433.3 1448.27
     486  1448.4   518.4 1448.95   550.8 1450.35   583.2 1450.97   656.2 1450.45
   724.3 1450.99   733.1  1451.3   743.3 1452.43   750.5 1452.73   768.6 1455.18
   780.6 1459.02   796.7 1463.26   818.1 1468.18   840.9 1472.87   857.9 1473.29
#Mann= 6 ,-1,0
       0     .06       0      80     .05       0   404.9    .045       0
   418.1     .05       0  488.65     .06       0  824.93     .05       0
Bank Sta=404.9,418.1
XS Rating Curve= 0 ,0
Exp/Cntr=0.3,0.1

Type RM Length L Ch R = 1 ,56      ,,,
XS GIS Cut Line= 4
2161921.17994689690251.8555654032161488.17197825690056.248813842
2161432.14207048690055.3324506192161079.38764249 690359.23307739
#Sta/Elev= 30
       0 1461.54      23 1458.87    63.3 1455.93    75.3 1454.22    97.7 1449.35
   110.8 1447.96   126.7 1447.11   176.7 1446.87   242.5 1447.39   286.4 1448.43
     304 1447.56   321.5 1447.39   475.1 1447.85   483.1 1447.49  490.851446.499
   499.1 1445.52   507.1 1446.49   527.1 1448.12   552.4 1448.09   580.7 1447.36
   625.9 1447.78   668.6 1447.56   730.1 1448.45   773.5  1450.4   842.6 1449.88
   911.3 1450.94   932.4 1452.12   957.9 1454.69   980.6 1455.59   996.8  1460.5
#Mann= 5 ,-1,0
       0     .06       0      90     .05       0  490.85    .045       0
   507.1     .05       0  931.18     .06       0
Bank Sta=490.85,507.1
XS Rating Curve= 0 ,0
Exp/Cntr=0.3,0.1
LCMann Table=0

Chan Stop Cuts=-1
Use User Specified Reach Order=0
Composite Channel Slope=5